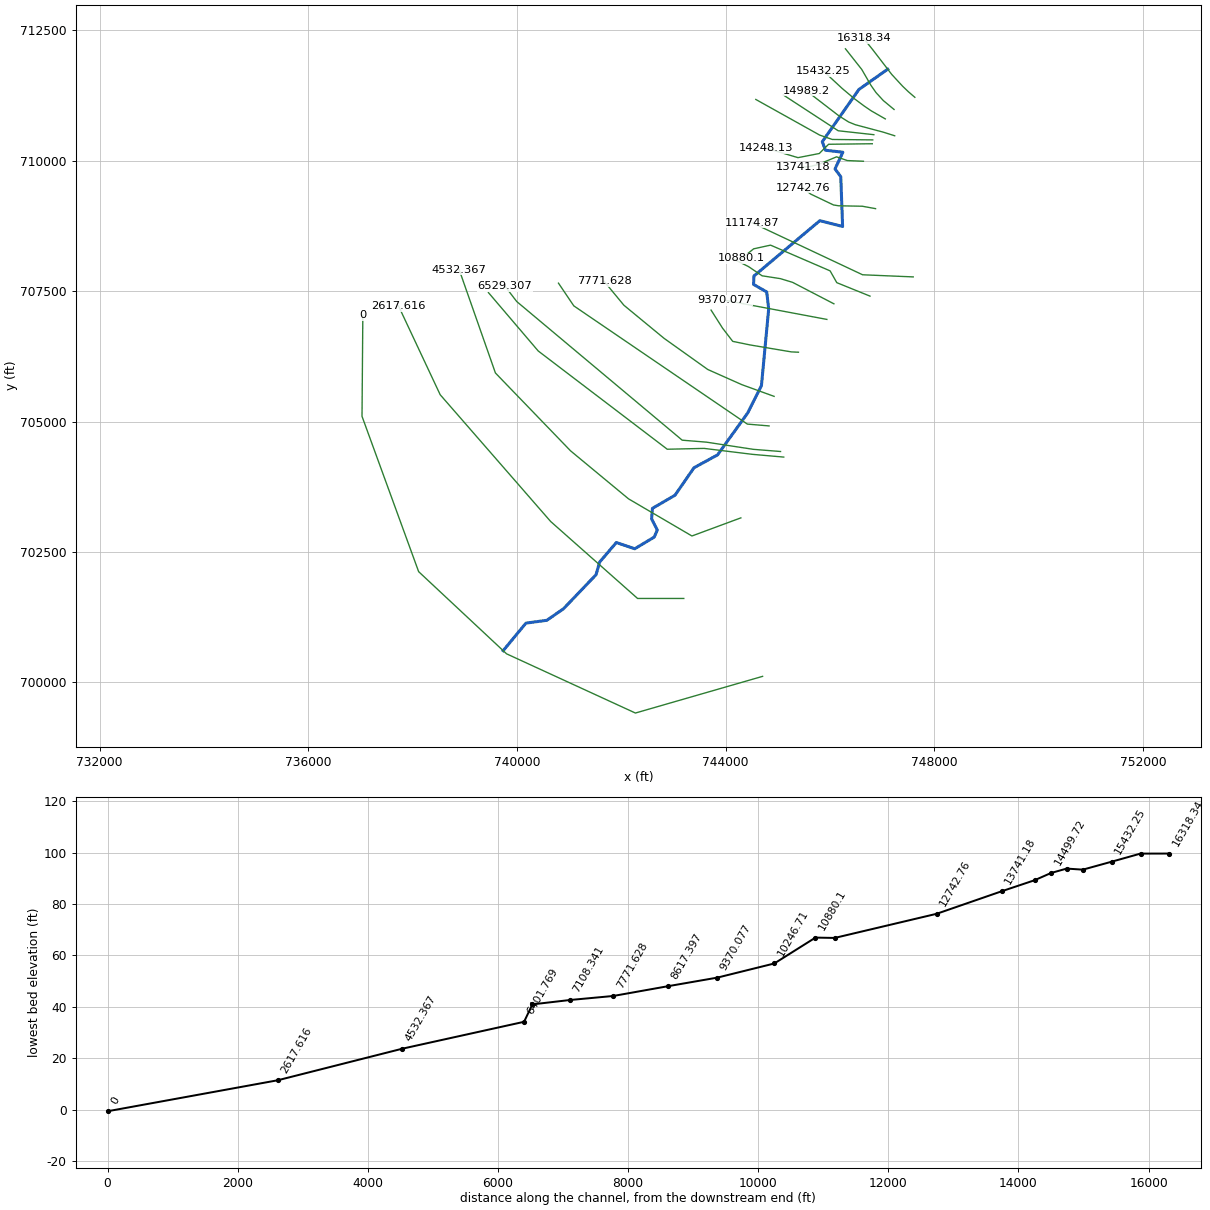
--- 6232_ras.prj (project) ---

Proj Title=6232
Current Plan=p01
Default Exp/Contr=0.3,0.1
English Units
Geom File=g01
Flow File=f01
Plan File=p01
Y Axis Title=Elevation
X Axis Title(PF)=Main Channel Distance
X Axis Title(XS)=Station
BEGIN DESCRIPTION:
RFD model 6232 exported to HEC-RAS
END DESCRIPTION:

--- 6232_ras.p01 (plan) ---

Plan Title=Plan 01
Program Version=4.10
Short Identifier=Plan 01
Geom File=g01
Flow File=f01
Subcritical Flow
Calc Critical at every XS
Secant Critical Depth

--- 6232_ras.f01 (steady flow) ---

Flow Title=Flow 01
Program Version=5.01
Number of Profiles= 6
Profile Names=10yr,25yr,50yr,100yr,100plus,500yr
River Rch & RM=6232,21,16318.34
 3753.22 6578.84 9452.2312318.2117984.5921953.47
River Rch & RM=6232,21,15875.29
 3757.72 6587.83 9466.1912337.6218012.9221988.01
River Rch & RM=6232,21,15432.25
 3763.33 6599.07 9483.6812361.9918048.5122031.53
River Rch & RM=6232,21, 14989.2
 3793.18 6659.04 9577.0812492.2118238.6322264.33
River Rch & RM=6232,21, 14740.6
 3795.41 6663.57 9584.1712502.1518253.1422282.25
River Rch & RM=6232,21,14499.72
 3797.84 6668.48 9591.8712512.9318268.8822301.66
River Rch & RM=6232,21,14248.13
 3804.93 6682.92 9614.5212544.7118315.2722359.12
River Rch & RM=6232,21,13741.18
 3808.45 6690.21 9626.0612560.9918339.0522388.94
River Rch & RM=6232,21,12742.76
 3824.09 6722.53 9677.1512633.0818444.2922520.72
River Rch & RM=6232,21,11174.87
 5011.86 8896.4212890.9516923.0924707.7129304.18
River Rch & RM=6232,21, 10880.1
 5019.16 8911.8312915.6116958.2524759.0529367.19
River Rch & RM=6232,21,10246.71
  5022.3 8918.49 12926.316973.5324781.3529394.65
River Rch & RM=6232,21,9370.077
 5035.29 8946.3212971.1817037.8524875.26 29511.1
River Rch & RM=6232,21,8617.397
 5089.29 9059.7113152.2617295.5225251.4629970.46
River Rch & RM=6232,21,7771.628
 5092.39 9066.5413163.4317311.71 25275.130000.37
River Rch & RM=6232,21,7108.341
 5106.05 9096.5713212.4717382.7125378.7630131.15
River Rch & RM=6232,21,6529.307
 5112.27  9110.513235.4217416.1625427.5930193.47
River Rch & RM=6232,21,6401.769
 5117.79 9123.07 13256.317446.7525472.2630251.11
River Rch & RM=6232,21,4532.367
 5213.54 9337.0813608.7717960.3826222.1631206.83
River Rch & RM=6232,21,2617.616
 5230.95 9377.1313675.6118058.7826365.8131393.06
River Rch & RM=6232,21,       0
 5269.23 9465.9613824.5518278.7626686.9931811.65
Boundary for River Rch & Prof#=6232,21,1
Up Type= 0
Dn Type= 2
Boundary for River Rch & Prof#=6232,21,2
Up Type= 0
Dn Type= 2
Boundary for River Rch & Prof#=6232,21,2
Up Type= 0
Dn Type= 2
Boundary for River Rch & Prof#=6232,21,2
Up Type= 0
Dn Type= 2
Boundary for River Rch & Prof#=6232,21,2
Up Type= 0
Dn Type= 2
Boundary for River Rch & Prof#=6232,21,2
Up Type= 0
Dn Type= 2

--- 6232_ras.g01 (geometry) ---

Geom Title=6232
Program Version=4.10

River Reach=6232,21
Reach XY= 30
747105.736581951711756.167799428746554.087276399711367.712938339
745852.264359742 710366.41085501 745913.89630416710202.782382801
746246.795609713710164.587938339746096.621998638709844.709466115
 746206.86505419709695.403910547746241.587276399 708741.41085498
745805.389359742708852.521966115744541.934498638 707792.19210501
 744534.99005419707630.299743876744786.726165265707487.070577204
744824.920609772707162.851827219744686.031720847705690.195577219
 744421.70880419705165.021966085743844.885887533704362.938632786
743392.628943056704115.976827204743029.347693056703589.935160533
742596.621998668703337.765021637742580.128943026703135.942104995
742689.503943026  702922.8344661742630.476165295702786.549743876
742257.212276369702563.025438324741904.347693056 702682.81710498
741584.469220847702308.685160547741515.024776399702065.195577204
740891.037507921701412.417799428740572.027091235701191.931688324
740170.860103875701137.139980495739735.221535683700609.900438309

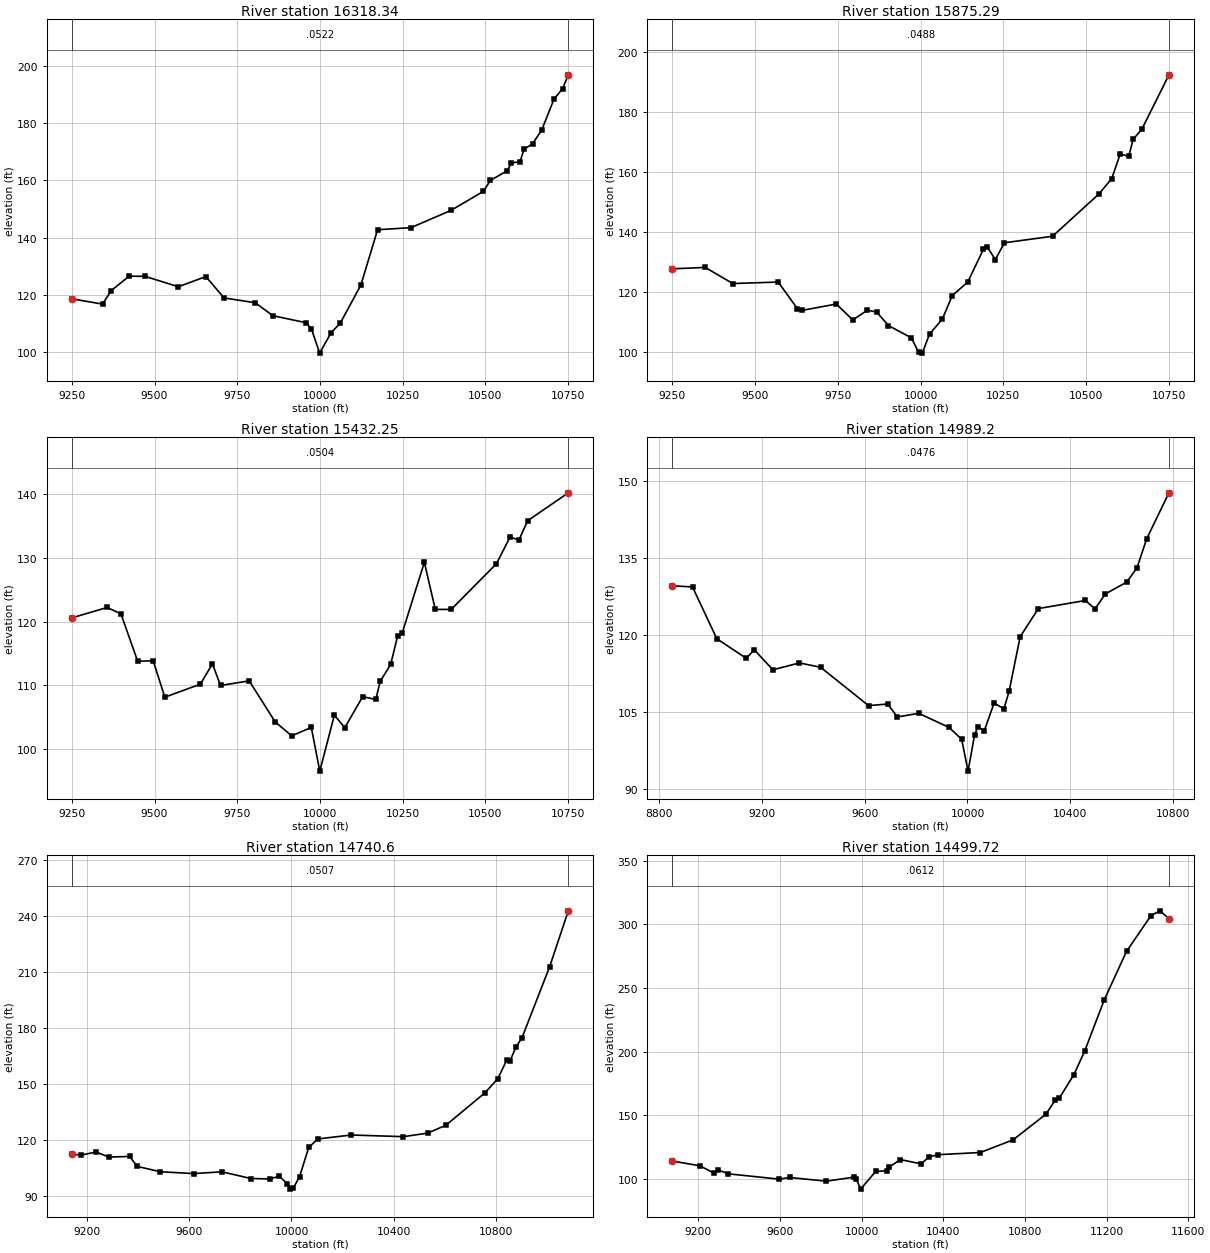
Type RM Length L Ch R = 1 ,16318.34,443.047400,443.047400,443.047400
XS GIS Cut Line= 6
 747626.72710842711217.811510743 747500.48676254711326.442501091
747395.665455178711426.743937862747184.609392982711655.292344498
746815.924516683712135.076867812746644.069674327712348.445073018
#Sta/Elev= 30
9249.049118.66159342.854116.80229369.312121.53349423.205126.56499471.382126.4925
9572.128122.86349655.251126.41879710.325118.94649804.306 117.2919858.009 112.746
9958.479 110.2969974.542108.0957 9999.2799.6811510033.97106.852910060.99110.0429
10123.91123.440210174.34142.7661 10275.2143.493910396.42149.530310494.59156.1862
 10515.2159.984110566.25 163.34910579.01166.179810604.54166.4078 10617.3170.8613
10643.06172.816810670.68177.602510707.73188.373110733.75192.057510750.99196.8629
#Mann= 3 , 0 , 0
9249.049  0.0522       09249.049  0.0522       010750.99  0.0522       0
#XS Ineff= 2 , 0
       0                               0
Bank Sta=9249.049,10750.99
Exp/Cntr=0.3,0.1

Type RM Length L Ch R = 1 ,15875.29,443.047300,443.047300,443.047300
XS GIS Cut Line= 6
747228.452706298710984.581054685747022.905786077711154.653135514
746881.045986311711309.766007791746785.223249938 711447.06010785
746609.097528999711751.904929318746296.434438243712147.540117693
#Sta/Elev= 30
9249.102 127.7429349.019128.20619432.372122.84279569.592123.33579627.856114.4597
9641.631113.89389745.391116.01539795.207110.71399839.438113.98499867.579113.3096
9903.081108.83179972.143104.76089994.24499.9129410005.1899.6623610027.13106.0004
10065.95111.010210095.75118.823410142.65123.343910190.07134.259810202.09134.8922
10226.14130.837810253.48136.414510399.07138.597610539.19152.667810577.85157.7965
10603.63166.000710629.44165.203510642.57170.877110668.84 174.22110750.95192.3614
#Mann= 3 , 0 , 0
9249.102  0.0488       09249.102  0.0488       010750.95  0.0488       0
#XS Ineff= 2 , 0
       0                               0
Bank Sta=9249.102,10750.95
Exp/Cntr=0.3,0.1

Type RM Length L Ch R = 1 ,15432.25,443.047300,443.047300,443.047300
XS GIS Cut Line= 6
747059.957629423710803.680400216746790.465412317710958.459875476
746653.018617675 711052.31539812746470.328136417711188.814989808
746234.969723179711386.314112672745876.008299307711718.778134882
#Sta/Elev= 30
9249.049 120.5839356.558122.23239398.456121.23699449.151113.78019496.023113.8601
9531.176108.13769638.525110.17429675.138113.37939699.546109.97319786.315110.7007
9864.516104.27249914.637102.06129974.039103.38099999.64896.5149110043.71105.3136
10075.26103.344210129.28108.2143   10169107.778810182.24110.610310213.93113.2818
10235.19117.803610248.43118.155110315.78129.330110348.86121.933710396.94121.9232
10533.59129.099810574.61133.267110601.96132.869910628.15135.868810750.99140.2505
#Mann= 3 , 0 , 0
9249.049  0.0504       09249.049  0.0504       010750.99  0.0504       0
#XS Ineff= 2 , 0
       0                               0
Bank Sta=9249.049,10750.99
Exp/Cntr=0.3,0.1

Type RM Length L Ch R = 1 , 14989.2,248.595400,248.595400,248.595400
XS GIS Cut Line= 6
747240.259023672710480.175549599747027.745984685710547.814534362
746483.575418715710693.037832765746356.744833105710744.747402801
746173.812463174710860.029682757745545.602640062711343.696371308
#Sta/Elev= 30
8851.147129.6019  8930.4129.37339024.678119.2761 9139.29115.43689170.422 117.108
9242.953113.20289346.051114.54219428.529113.69249615.142106.20049689.427106.5169
9727.496 103.9959810.489104.6963 9928.32101.94959977.30999.6475910002.2393.41269
10027.57100.455910040.24102.045410065.58  101.32 10103.6106.706610141.61105.5797
10161.86108.974610204.96119.655210275.84125.152710458.38126.729410496.39125.0936
10536.38128.011610619.53130.317310659.56133.111710697.08138.772210783.87147.7528
#Mann= 3 , 0 , 0
8851.147  0.0476       08851.147  0.0476       010783.87  0.0476       0
#XS Ineff= 2 , 0
       0                               0
Bank Sta=8851.147,10783.87
Exp/Cntr=0.3,0.1

Type RM Length L Ch R = 1 , 14740.6,240.884200,240.884200,240.884200
XS GIS Cut Line= 3
746840.880339235  710501.2005191746157.547005862  710576.2005191
745103.380339205  711263.7005191
#Sta/Elev= 30
9138.389112.66119174.485111.96859234.845113.68259285.145110.95359365.626111.3155
9395.806105.98539486.346103.11399617.127102.14249727.787103.08299840.80599.50901
9915.15899.24619 9951.77100.7208 9984.0796.716659996.00993.8288110006.6994.24173
10031.82100.529710067.64116.143810103.46120.663810234.78122.769710437.74121.8742
10533.25123.750810604.88127.989110757.24145.227210807.84152.808510843.66162.9051
 10855.6 162.31510879.47169.761310903.35174.8733 11010.8212.529311084.37242.6112
#Mann= 3 , 0 , 0
9138.389  0.0507       09138.389  0.0507       011084.37  0.0507       0
#XS Ineff= 2 , 0
       0                               0
Bank Sta=9138.389,11084.37
Exp/Cntr=0.3,0.1

Type RM Length L Ch R = 1 ,14499.72,251.586400,251.586400,251.586400
XS GIS Cut Line= 4
746820.047005892710401.200519115746045.047005862710409.533852458
745803.380339205710492.867185786744578.380339235  711176.2005191
#Sta/Elev= 30
9072.294114.16829207.349110.46129277.353104.71199297.354  107.199347.357 104.109
9597.37199.935269647.374 101.2559827.38598.345759963.745101.54889974.32399.97511
9995.47892.1092410069.52106.080410124.02 106.48110135.47109.343610189.46115.3329
10292.09 111.91910330.13 117.45110375.93119.161210582.04120.853210742.35130.8083
10902.66150.879810948.46  161.88 10969.5163.778111040.07181.984111092.66200.3413
11188.92240.778611297.93278.713611417.94306.870611462.15 310.54511505.67304.3578
#Mann= 3 , 0 , 0
9072.294  0.0612       09072.294  0.0612       011505.67  0.0612       0
#XS Ineff= 2 , 0
       0                10363.67       0
Bank Sta=9072.294,11505.67
Exp/Cntr=0.3,0.1

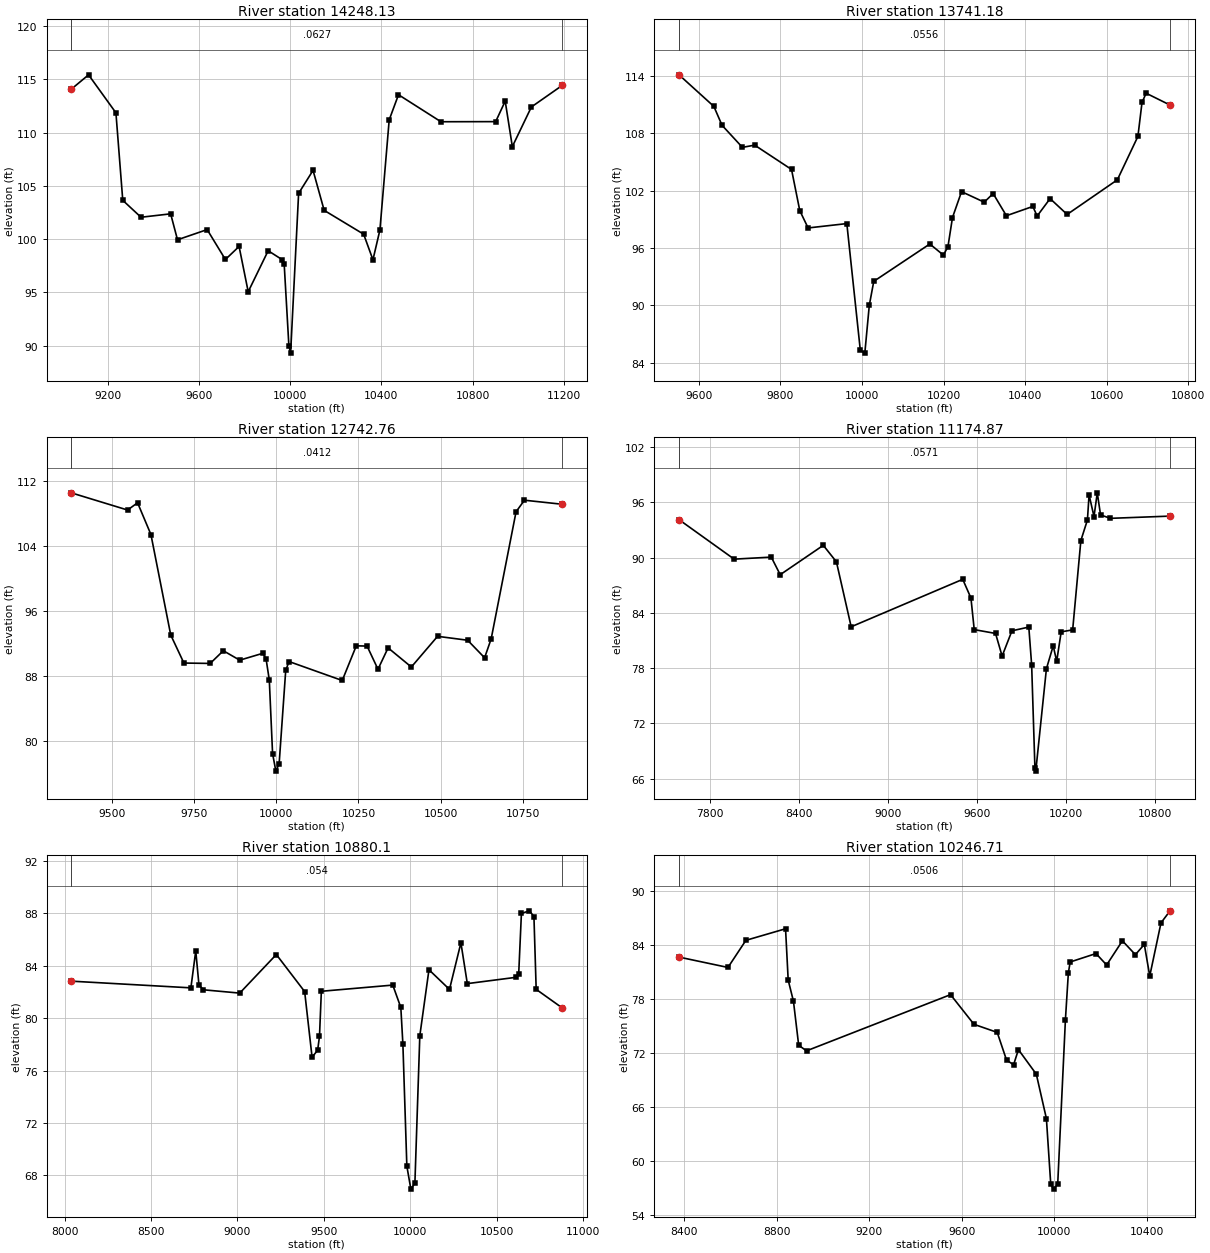
Type RM Length L Ch R = 1 ,14248.13,506.957100,506.957100,506.957100
XS GIS Cut Line= 5
746811.019228101 710327.58940801745973.519228131710317.172741339
745794.352561414 710140.08940801745386.019228101710060.922741339
744765.185894787710246.339407995
#Sta/Elev= 30
9039.613114.08529115.638115.43869235.648111.8697 9265.65103.65219345.656102.0627
9475.666102.38269505.66899.945829635.678100.90349715.68598.094419775.68999.31901
9815.69295.065529903.216 98.91699965.62298.066799973.51797.654159994.07390.00115
10001.6489.3006110036.75104.306110100.06106.4662 10148.8102.710210321.97100.4704
10362.7198.0661310393.27100.868410434.02111.212610474.76  113.5710660.89111.0325
10900.93111.042610942.67112.970110973.98108.695311057.48112.419111192.96114.4485
#Mann= 3 , 0 , 0
9039.613  0.0627       09039.613  0.0627       011192.96  0.0627       0
#XS Ineff= 2 , 0
       0                10113.09       0
Bank Sta=9039.613,11192.96
Exp/Cntr=0.3,0.1

Type RM Length L Ch R = 1 ,13741.18,998.418500,998.418500,998.418500
XS GIS Cut Line= 6
746640.455367919709991.830414593746332.688480716710004.985970169
746125.994606041710076.409437938745774.705091309 709929.87054734
745619.502308418 709891.44082858745486.459406746709877.541936102
#Sta/Elev= 30
9551.448114.09769636.905110.79419656.906108.82369706.914106.51149736.926106.7458
9827.334104.20259847.56799.897459867.95298.084259962.92498.540449996.03985.27861
10007.0484.99355   1001889.9879710028.9792.50062 10166.496.4062310199.7695.24618
10210.88 96.1279   1022299.1737110244.24101.880310299.84100.779710321.68101.6819
10354.1799.3611110418.97100.333910429.5699.3325110461.34101.1522 10503.199.49699
10626.22103.117610676.63107.654110686.72111.2117 10696.8112.174510755.51110.9354
#Mann= 3 , 0 , 0
9551.448  0.0556       09551.448  0.0556       010755.51  0.0556       0
#XS Ineff= 2 , 0
       0                10388.82       0
Bank Sta=9551.448,10755.51
Exp/Cntr=0.3,0.1

Type RM Length L Ch R = 1 ,12742.76,1567.892400,1567.892400,1567.892400
XS GIS Cut Line= 6
746873.838156819709083.241093665746619.082690626709129.509209752
746165.688273758709138.034115583746067.786080301709153.811432213
745629.392623991709363.017721698745474.683393449709485.553964928
#Sta/Elev= 30
 9375.28110.5203 9546.88108.4011 9577.37109.29259618.025105.38319678.36492.99909
9718.43689.544789798.50389.497039838.50791.061089888.51189.899239958.51790.74294
9968.51890.095329978.51987.469049988.51978.38355 9998.5276.2264410008.5277.14891
10028.5288.6271210038.5389.7315110200.6587.3942510243.4591.6689910276.3591.63508
 10309.588.7808910340.3591.4153410411.1389.0582410491.03 92.837110582.6392.35447
10634.2490.19452 10654.392.5330910730.08108.1898 10755.6109.610810870.81109.1109
#Mann= 3 , 0 , 0
 9375.28  0.0412       0 9375.28  0.0412       010870.81  0.0412       0
#XS Ineff= 2 , 0
       0                               0
Bank Sta=9375.28,10870.81
Exp/Cntr=0.3,0.1

Type RM Length L Ch R = 1 ,11174.87,294.760800,294.760800,294.760800
XS GIS Cut Line= 3
747596.108040482707774.706037536746624.703793645707815.521342009
744511.268482059 708810.27610448
#Sta/Elev= 30
7591.48194.129517962.91689.840228213.137 90.0604 8273.1988.151338563.44691.34111
8651.83489.549058751.30582.495999502.86387.649269558.12585.61609 9580.2382.18683
 9723.9181.773299768.119  79.3149834.43382.05955 9947.9382.464029967.06178.36192
9989.16667.157129994.89366.8217310066.53  77.936 10112.380.4248710135.7878.75003
   1016681.9443910243.37 82.160310298.6391.8605610342.8494.0952710353.8996.82875
10387.0594.4633610409.1597.0413210431.2694.6429610497.57 94.271410899.5894.51331
#Mann= 3 , 0 , 0
7591.481  0.0571       07591.481  0.0571       010899.58  0.0571       0
#XS Ineff= 2 , 0
       09711.081                       0
Bank Sta=7591.481,10899.58
Exp/Cntr=0.3,0.1

Type RM Length L Ch R = 1 , 10880.1,633.393000,633.393000,633.393000
XS GIS Cut Line= 6
746767.693350255707406.191161424746130.491476715707664.269339621
746002.594326437707890.373230249744860.655484915708383.690809771
744536.344853967708312.890601605744305.673207939708127.896509275
#Sta/Elev= 30
 8038.3982.827918730.77782.316668758.91485.135558777.55282.530138803.40782.16867
9013.41681.916129225.14384.860749388.98582.033929431.94777.025779464.16877.55475
9474.90978.624389485.64982.055399898.96682.527599945.47980.819629957.38578.03528
9980.363 68.706210003.6266.9555210026.8867.4053810055.3678.6657710108.2783.69821
10227.0182.1978410293.1485.7531110330.2182.6403510611.6483.1205110627.5583.39507
 10643.287.9989310689.63 88.195610715.6387.7615910728.6382.2030410879.6580.78263
#Mann= 3 , 0 , 0
 8038.39   0.054       0 8038.39   0.054       010879.65   0.054       0
#XS Ineff= 2 , 0
       09739.899                       0
Bank Sta=8038.39,10879.65
Exp/Cntr=0.3,0.1

Type RM Length L Ch R = 1 ,10246.71,876.634500,876.634500,876.634500
XS GIS Cut Line= 6
746075.111792943707258.918480165745281.828980813707670.863164818
745047.354799284707741.787820269744699.133541511707795.672739793
744439.692241396707971.451816668744159.557075913708112.574674596
#Sta/Elev= 30
8378.59882.638588590.09181.488618667.44484.499988838.79485.783698850.191 80.0859
8872.971 77.72988895.51272.849178929.32372.227989551.51678.468049652.674 75.1739
9753.149 74.27589793.31871.204249823.82970.680219844.66272.364079922.00469.63299
9965.52264.709689984.38357.389489997.03456.87158 10014.457.4421910047.7175.69947
10060.3780.8764110068.2282.0949710179.7183.0315810225.6881.7630810293.8484.44722
10349.8882.9065110388.5484.0492210411.9180.5380510460.5286.4395410499.7387.77654
#Mann= 3 , 0 , 0
8378.598  0.0506       08378.598  0.0506       010499.73  0.0506       0
#XS Ineff= 2 , 0
       09506.081                       0
Bank Sta=8378.598,10499.73
Exp/Cntr=0.3,0.1

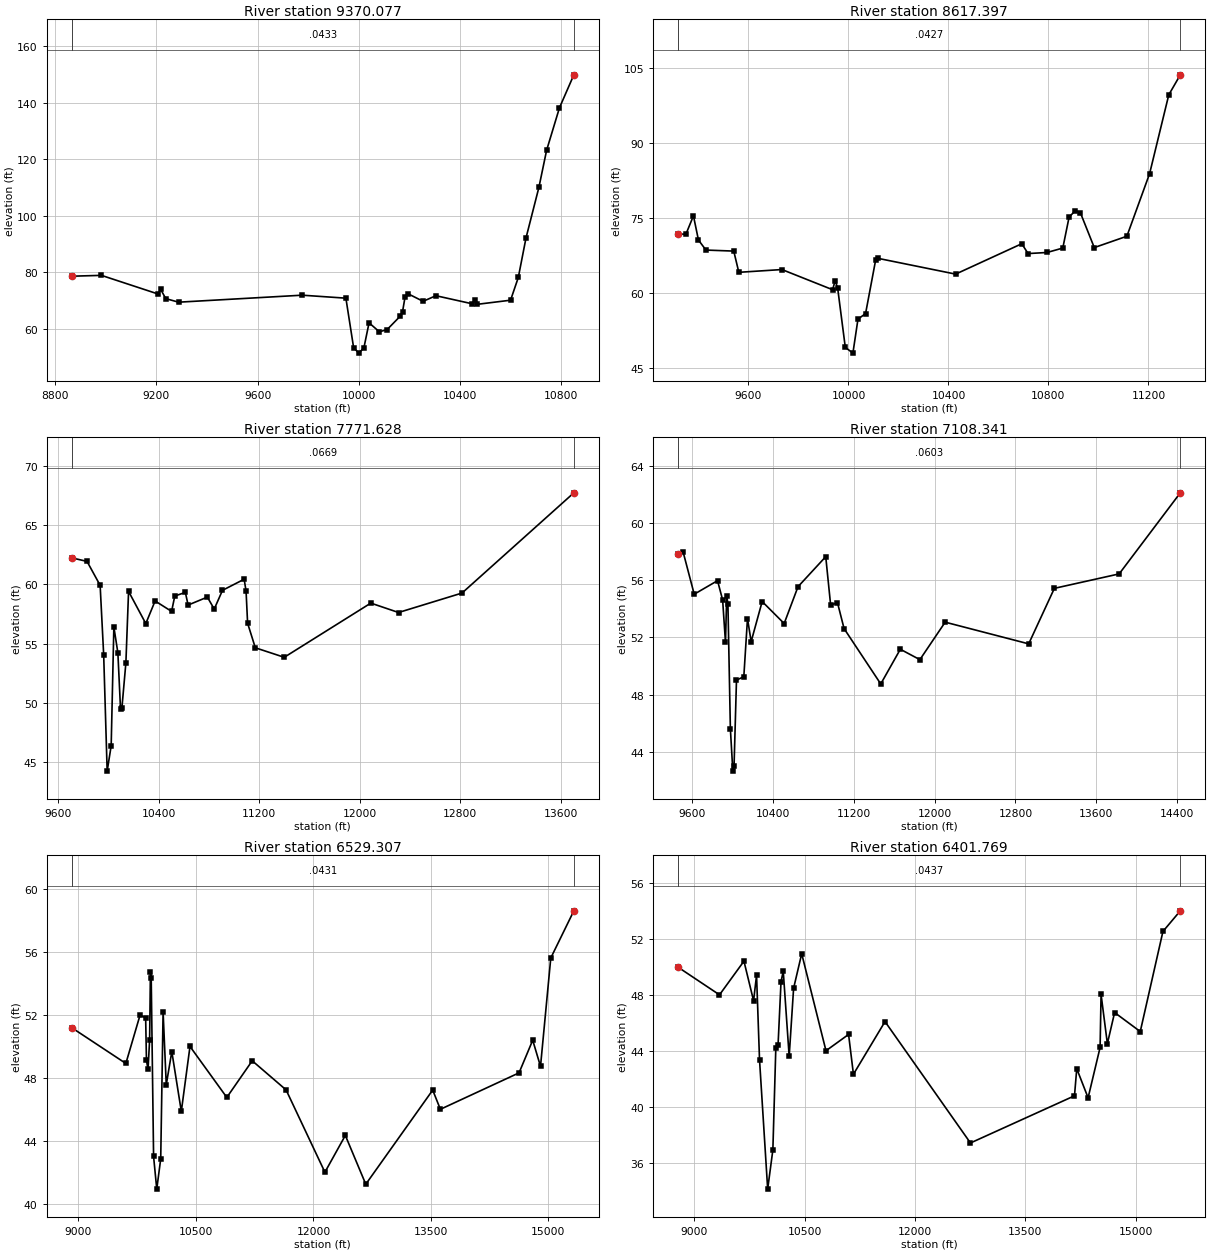
Type RM Length L Ch R = 1 ,9370.077,752.680800,752.680800,752.680800
XS GIS Cut Line= 2
745940.304940373 706959.85710074743989.120545357707326.276705444
#Sta/Elev= 30
8865.15878.589538982.47878.883889206.324 72.28939216.49973.961279236.84970.64595
9287.72369.393859776.11371.867779949.085 70.81499979.60953.303389999.95951.36066
10020.3153.2510310040.6662.0902810081.3658.9209310111.8859.6742910162.7664.33458
10172.9365.9548310183.11 71.297410193.2872.4400310254.3369.70244 10305.271.68106
10447.6568.8413610457.8270.21201   10468 68.632410600.2770.09492 10630.878.13682
10661.3292.14244 10712.2110.003210742.72123.146210793.59138.204410850.45149.8651
#Mann= 3 , 0 , 0
8865.158  0.0433       08865.158  0.0433       010850.45  0.0433       0
#XS Ineff= 2 , 0
       09802.197                       0
Bank Sta=8865.158,10850.45
Exp/Cntr=0.3,0.1

Type RM Length L Ch R = 1 ,8617.397,845.768700,845.768700,845.768700
XS GIS Cut Line= 6
745395.763629019 706330.87871784745259.360954583706337.077573076
744466.926701874 706470.74118194744135.646653801 706539.10055694
743941.085355759706791.504403085743720.231990337707138.559691578
#Sta/Elev= 30
 9319.01 71.82489349.80671.801239379.837 75.47349399.857  70.6359429.88868.63082
9541.10768.426279561.38964.18769 9733.7964.741219936.61660.712089946.75762.53986
9956.89860.985639987.32249.1971110017.7548.0472810038.0354.8369810068.4555.95441
10109.02 66.716410119.1666.96689 10428.763.8271810693.2769.8951110718.52 67.9314
10794.28 68.147410857.41 69.031410882.6675.2295510907.9276.5082910927.4676.12153
10983.34  69.12611113.7371.3920411204.7583.9138411281.3699.63822 11327.5 103.629
#Mann= 3 , 0 , 0
 9319.01  0.0427       0 9319.01  0.0427       0 11327.5  0.0427       0
#XS Ineff= 2 , 0
       09650.466        10253.64       0
Bank Sta=9319.01,11327.5
Exp/Cntr=0.3,0.1

Type RM Length L Ch R = 1 ,7771.628,663.286600,663.286600,663.286600
XS GIS Cut Line= 6
744928.516063392705484.846943364744311.072257012705708.612216577
743657.432680756705999.641845599742820.167326212706596.446850941
 742049.31969738707231.535466865741668.239534169707692.264046997
#Sta/Elev= 30
9707.05262.240839828.473  61.9439932.88659.918719961.062 54.05479988.83944.22035
 10020.846.3646110042.0956.4079710074.0454.2251310095.33 49.444510105.9849.53197
10137.9253.3770410159.2259.4095110296.4556.6883810370.5358.5995110501.8857.71609
10527.0959.0162710611.3559.3234610633.2458.2533510786.4958.9263910841.2257.91455
 10906.959.4984411079.3860.4360111094.6559.4401611106.9356.7201611168.3354.64301
11398.7253.8392612087.8658.4188812308.6257.6243912813.9459.2684113704.2667.73708
#Mann= 3 , 0 , 0
9707.052  0.0669       09707.052  0.0669       013704.26  0.0669       0
#XS Ineff= 2 , 0
       0  9830.9        10747.77       0
Bank Sta=9707.052,13704.26
Exp/Cntr=0.3,0.1

Type RM Length L Ch R = 1 ,7108.341,579.033900,579.033900,579.033900
XS GIS Cut Line= 4
744832.564681739704918.002546072744415.717039794704953.104728431
741088.651005566 707219.77096656 740795.12646994707654.911616459
#Sta/Elev= 30
9462.25957.827059509.99257.989759620.38155.020479851.19555.967249901.70954.61914
 9929.8551.65054 9941.9554.91013 9954.0554.339959978.25145.6217610002.4542.65664
10014.5542.9841610038.7549.0152510111.3549.2588510147.65 53.321310183.95 51.7079
10292.86 54.510110510.6652.9722710647.6755.5462110922.0657.6446110970.4754.26707
11038.4154.4248711103.5752.6183711466.5748.7487311660.1851.1744611853.7850.44772
12104.0653.0670812930.6951.55125 13184.855.4306413826.1156.4404614431.28 62.1063
#Mann= 3 , 0 , 0
9462.259  0.0603       09462.259  0.0603       014431.28  0.0603       0
#XS Ineff= 2 , 0
       09894.825        10868.56       0
Bank Sta=9462.259,14431.28
Exp/Cntr=0.3,0.1

Type RM Length L Ch R = 1 ,6529.307,127.538000,127.538000,127.538000
XS GIS Cut Line= 6
745051.933233947704427.649892375744530.848132759704469.109217614
743632.931466013704606.609217629743167.088275492704644.647944584
739994.833503544707302.483023822739767.934629679707598.882970616
#Sta/Elev= 30
8914.33551.202749604.84948.933949786.947  52.0199857.76351.815299867.87949.12982
9888.113 48.55729908.34650.440899918.46254.725369928.57954.373529958.92943.02621
9999.39540.9538410049.9842.8744510080.3352.2089810120.79 47.584910191.6149.68907
10313.0145.8888210423.6450.0148110893.8446.7769511218.2449.1040411650.5147.25565
12146.26 42.027712407.1844.36407 12668.1 41.264413522.7547.2435513620.4546.02257
14624.9948.3372314799.5750.4109914898.9648.7481715030.0955.6293815324.6358.62592
#Mann= 3 , 0 , 0
8914.335  0.0431       08914.335  0.0431       015324.63  0.0431       0
#XS Ineff= 2 , 0
       09796.266        11321.65       0
Bank Sta=8914.335,15324.63
Exp/Cntr=0.3,0.1

Type RM Length L Ch R = 1 ,6401.769,1869.402900,1869.402900,1869.402900
XS GIS Cut Line= 6
745113.616438836 704320.57715936744511.403688282704373.275884226
743586.403688341704487.164773151742880.629942149 704471.03683348
740406.671608865706354.717389032739451.810497731707474.509055704
#Sta/Elev= 30
8783.35250.004599344.10348.039369676.43250.443279807.41447.615349847.71649.44071
9888.01843.412789998.848 34.166810069.3836.9659810109.6844.2573910139.9144.44895
10180.2148.9651210210.4349.7329410291.0443.6480410351.2648.5087110461.2950.97521
10791.3844.0465211098.3845.2114511164.4142.36955 11593.646.12874 12754.837.46211
14168.6740.8300714199.4942.7665914353.6140.6870414516.7544.28573 14529.948.06738
14615.6144.5519314713.8846.7750815062.5645.41808 15370.852.5654115606.8954.03723
#Mann= 3 , 0 , 0
8783.352  0.0437       08783.352  0.0437       015606.89  0.0437       0
#XS Ineff= 2 , 0
       0 9744.36         11608.6       0
Bank Sta=8783.352,15606.89
Exp/Cntr=0.3,0.1

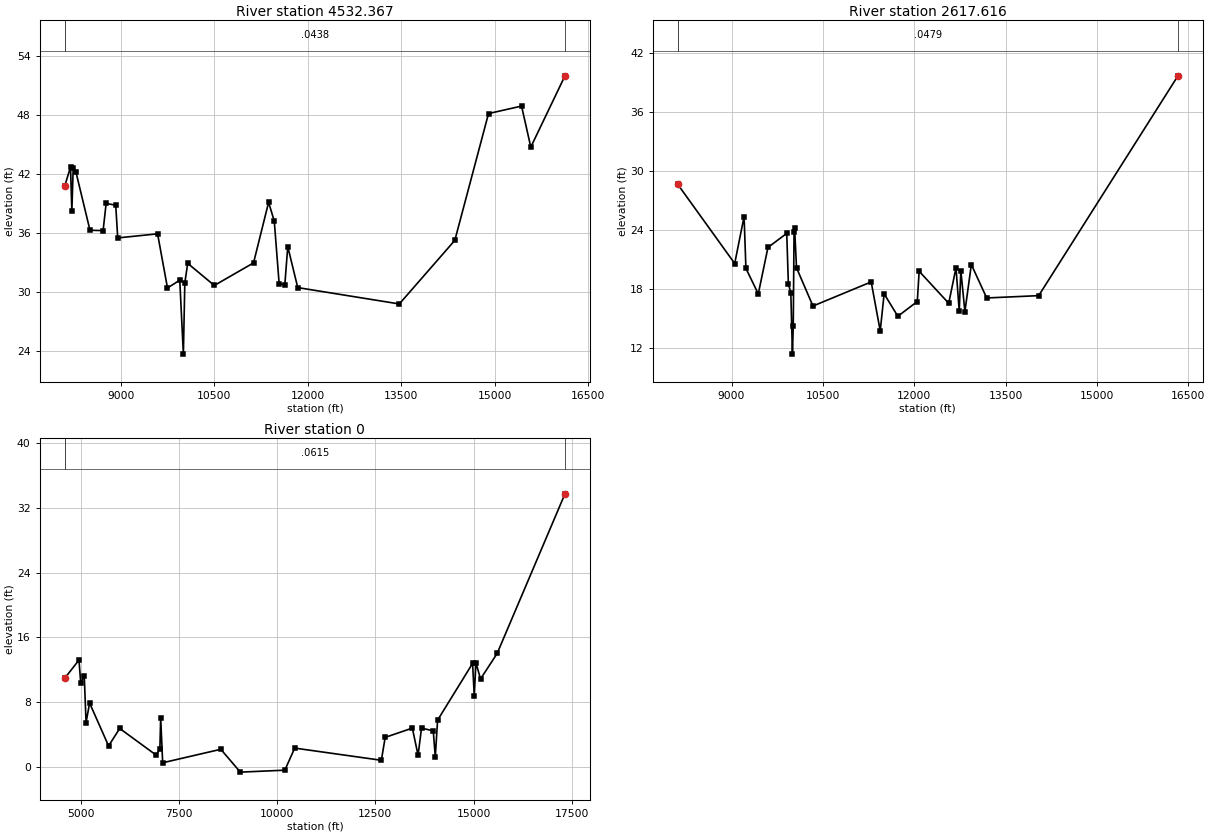
Type RM Length L Ch R = 1 ,4532.367,1914.750100,1914.750100,1914.750100
XS GIS Cut Line= 6
744291.061984986703155.269761011743353.561984986702808.047538787
742138.284207225703519.853094354741027.173096091 704439.99198322
739586.200873882705933.047538772738891.756429434707912.214205444
#Sta/Elev= 30
8102.92640.792498194.70142.700878216.02938.211248237.35742.563218280.01242.23024
8506.79636.282948717.229 36.24178765.92739.005928919.84238.822268951.83435.50228
9591.28635.916839749.98130.421049946.99531.2079510004.94 23.704410028.1230.94164
10074.4732.9205810501.4530.6751411130.5932.9683311372.2539.1217211463.1337.20142
11541.0430.86726 11632.330.7404311679.3434.6221111839.6630.4586113468.8328.79867
14359.2935.2562614899.7848.1272315429.6648.8875415578.0344.7216316126.1651.95812
#Mann= 3 , 0 , 0
8102.926  0.0438       08102.926  0.0438       016126.16  0.0438       0
#XS Ineff= 2 , 0
       09168.122        11169.45       0
Bank Sta=8102.926,16126.16
Exp/Cntr=0.3,0.1

Type RM Length L Ch R = 1 ,2617.616,2617.616400,2617.616400,2617.616400
XS GIS Cut Line= 5
743197.311984986 701610.13087213742311.895318359 701610.13087213
740645.228651643703085.825316578738527.173096091 705516.38087213
737728.561985016707217.769761011
#Sta/Elev= 30
 8117.22 28.62849051.91620.604179206.08625.362139236.25620.107519439.25417.52167
9598.29622.234179906.732 23.66139933.44518.513229973.51517.6580110000.2311.40951
10013.5814.2475710026.9423.8344610035.7624.2419410067.0120.1726910337.46 16.2901
11293.9518.7358311442.1713.7658611506.1717.5260111731.3715.2497312051.0116.74651
12081.4619.8179112567.3116.5658512686.6920.1777612739.7415.7615512766.2719.88311
12832.5915.7209412938.71 20.499213190.73 17.107814044.9917.3429516332.1539.64482
#Mann= 3 , 0 , 0
 8117.22  0.0479       0 8117.22  0.0479       016332.15  0.0479       0
#XS Ineff= 2 , 0
       09725.867        12316.24       0
Bank Sta=8117.22,16332.15
Exp/Cntr=0.3,0.1

Type RM Length L Ch R = 1 ,       0,0.000000,0.000000,0.000000
XS GIS Cut Line= 6
744707.728651643700117.075316563742269.935220063699413.904467881
739799.385067344700549.324905947738114.325164646702124.458214566
737028.746016979705102.046733782737044.472221822707041.202426448
#Sta/Elev= 30
4597.95510.944484958.77713.185745003.49810.310065092.94111.243915139.2525.446388
5228.6957.8758565712.132 2.569035995.529 4.726996926.6921.4197827017.7842.245833
7038.0276.0491057088.6330.4856388568.3312.152745 9065.28-0.67079 10197.6-0.43048
10448.852.29974112654.390.79352812751.213.62424613443.064.77288813588.621.405027
 13676.24.77838213975.264.42314414026.541.17935314084.935.75057714975.7812.77025
15018.368.77155415060.9312.8535315178.0110.8463715600.7113.9974517326.9733.72967
#Mann= 3 , 0 , 0
4597.955  0.0615       04597.955  0.0615       017326.97  0.0615       0
#XS Ineff= 2 , 0
       09392.339        12696.68       0
Bank Sta=4597.955,17326.97
Exp/Cntr=0.3,0.1